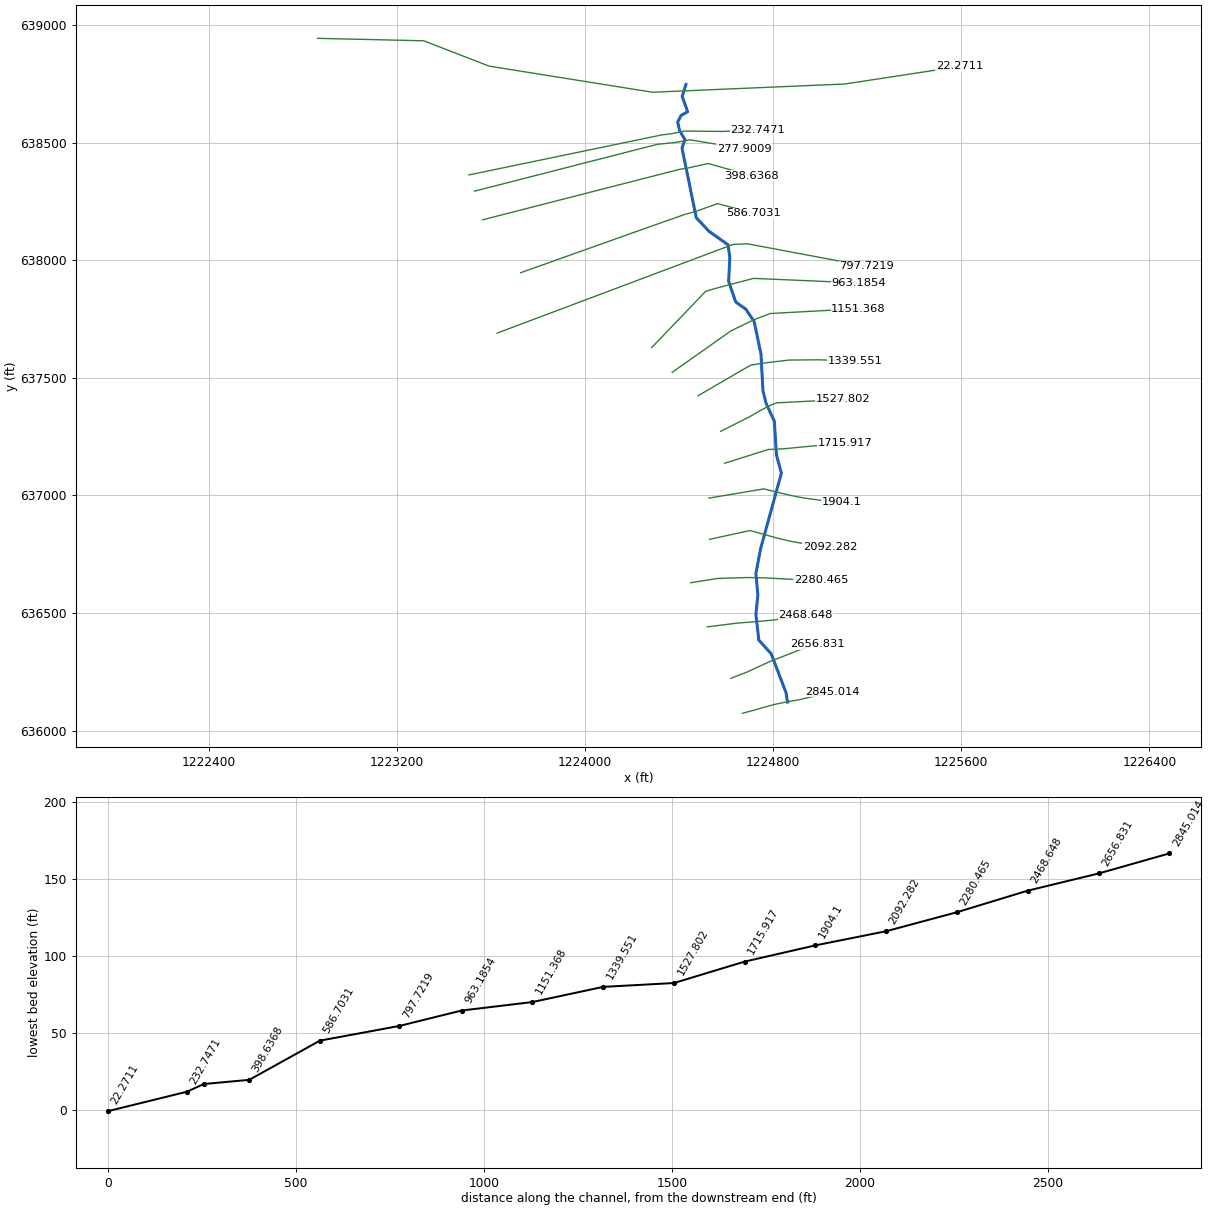
--- 560_ras.prj (project) ---

Proj Title=560
Current Plan=p01
Default Exp/Contr=0.3,0.1
English Units
Geom File=g01
Flow File=f01
Plan File=p01
Y Axis Title=Elevation
X Axis Title(PF)=Main Channel Distance
X Axis Title(XS)=Station
BEGIN DESCRIPTION:
RFD model 560 exported to HEC-RAS
END DESCRIPTION:

--- 560_ras.p01 (plan) ---

Plan Title=Plan 01
Program Version=4.10
Short Identifier=Plan 01
Geom File=g01
Flow File=f01
Subcritical Flow
Calc Critical at every XS
Secant Critical Depth

--- 560_ras.f01 (steady flow) ---

Flow Title=Flow 01
Program Version=5.01
Number of Profiles= 5
Profile Names=10yr,25yr,50yr,100yr,500yr
River Rch & RM=560,17,2845.014
  362.24  428.48  509.84  539.17  625.33
River Rch & RM=560,17,2468.648
  382.61  456.21  543.82  579.78  679.44
River Rch & RM=560,17,2280.465
  491.15  607.39  730.06  807.61  992.37
River Rch & RM=560,17,2092.282
  495.96  614.21   738.5  818.13 1007.15
River Rch & RM=560,17,  1904.1
  507.11  630.06  758.12  842.63  1041.7
River Rch & RM=560,17,1715.917
  516.78  643.85  775.19  864.02 1071.97
River Rch & RM=560,17,1527.802
  524.53  654.94  788.93  881.27 1096.47
River Rch & RM=560,17,1339.551
  554.94  698.64  843.15  949.72 1194.33
River Rch & RM=560,17,1151.368
  560.43  706.56  852.99   962.2 1212.29
River Rch & RM=560,17,963.1854
  568.26  717.89  867.07   980.1  1238.1
River Rch & RM=560,17,797.7219
  569.71     720  869.68  983.42 1242.89
River Rch & RM=560,17,586.7031
  574.99  727.64  879.18  995.52 1260.38
River Rch & RM=560,17,398.6368
   578.3  732.45  885.16 1003.15 1271.43
River Rch & RM=560,17,277.9009
  581.59  737.22   891.1 1010.72 1282.41
River Rch & RM=560,17, 22.2711
  582.99  739.26  893.63 1013.95  1287.1
Boundary for River Rch & Prof#=560,17,1
Up Type= 0
Dn Type= 2
Boundary for River Rch & Prof#=560,17,2
Up Type= 0
Dn Type= 2
Boundary for River Rch & Prof#=560,17,2
Up Type= 0
Dn Type= 2
Boundary for River Rch & Prof#=560,17,2
Up Type= 0
Dn Type= 2
Boundary for River Rch & Prof#=560,17,2
Up Type= 0
Dn Type= 2

--- 560_ras.g01 (geometry) ---

Geom Title=560
Program Version=4.10

River Reach=560,17
Reach XY= 30
1224861.05586302636121.1064233631224855.22253251636160.273078561
1224791.88922271636326.9396976081224739.38923988636384.439682066
1224726.88924679 636495.272982881224735.22257999 636575.27295889
 1224726.8892518636667.7729316951224746.88924894636772.772899926
1224835.22256553637094.4394685781224814.38924059637171.106113091
1224805.22258079637316.1060702951224770.22259334637391.106049076
1224756.88926548637445.2727001161224748.55593911637600.272654325
1224719.38928515637739.4392804951224683.55596387637791.939265981
1224641.05597728637821.9392583221224611.05598867637910.272566289
1224616.05599016638011.1058695761224608.55599394638065.272520363
1224528.30970255638122.0329354411224473.51726875638180.048453599
1224412.72273034638476.9390705081224425.22272769638512.772392884
 1224402.7227354638550.2723823791224394.38940558638586.939038411
1224408.55606893638615.2723629921224436.88939431638631.105690747
1224413.55606973638696.1056721211224429.38939989638746.938989952

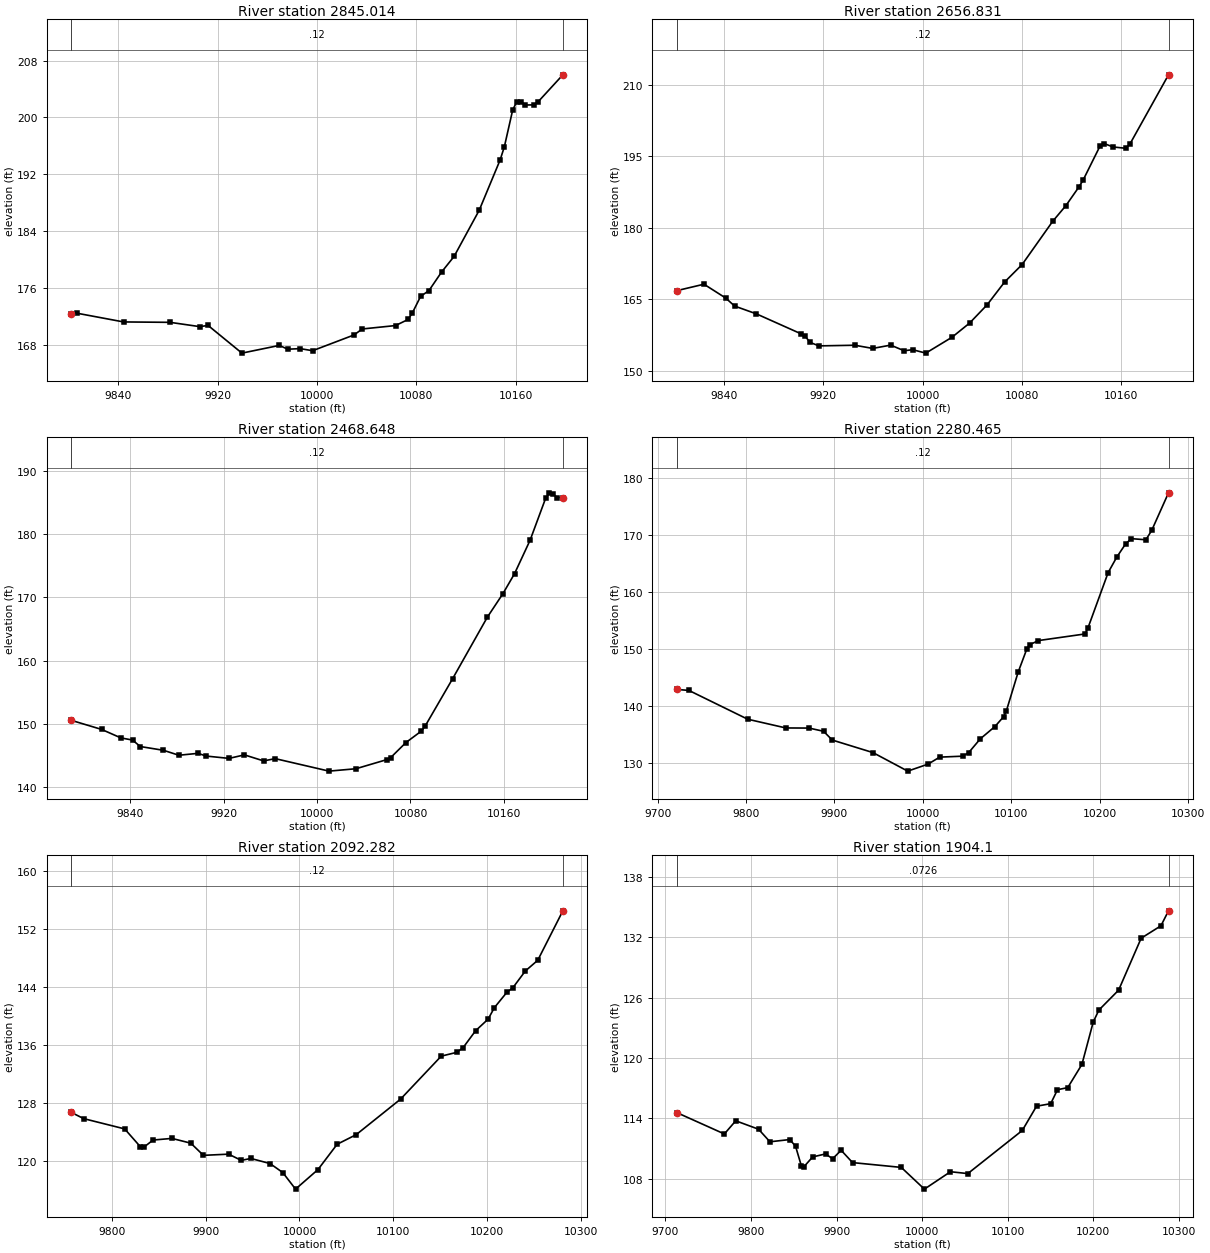
Type RM Length L Ch R = 1 ,2845.014,188.182900,188.182900,188.182900
XS GIS Cut Line= 6
1224669.13576581636073.1165153771224807.01442207636111.525260904
1224859.91946157 636121.948202271224861.89764193636122.242824821
1224914.93915097636131.9956432091225054.18063557636165.164625046
#Sta/Elev= 30
 9801.95172.36629806.652 172.4149844.115171.18889881.578171.13169905.418170.5291
 9912.23170.69219939.476166.79439969.673167.8835 9976.36167.34629986.392 167.428
9996.424 167.13510029.78169.353610036.45170.197110063.23170.677610073.34171.5338
10076.72172.426610083.46174.789910090.21175.613110100.32178.209610110.44 180.422
10130.68186.926210147.54 194.01810150.91195.846710157.66201.058210161.03202.2342
 10164.4 202.23910167.78201.751210174.52201.7672 10177.9202.158710198.07206.0019
#Mann= 3 , 0 , 0
 9801.95    0.12       0 9801.95    0.12       010198.07    0.12       0
#XS Ineff= 2 , 0
       0                               0
Bank Sta=9801.95,10198.07
Exp/Cntr=0.3,0.1

Type RM Length L Ch R = 1 ,2656.831,188.182800,188.182800,188.182800
XS GIS Cut Line= 6
1224620.53098759636222.0942361841224690.25944995636249.207309131
1224786.99615098636294.0145702441224801.64836148636299.438166516
 1224910.7195028636342.4230464231224988.57497668636367.538709603
#Sta/Elev= 30
9801.952166.8389 9823.76168.18489841.361165.26729848.401163.60739866.002161.9628
9901.867157.79249905.482157.23279909.098155.99979916.329155.24919945.255155.3849
9959.718154.7187 9974.18155.40939984.974154.23519991.971154.445110002.49153.7301
10023.65 157.07110037.76160.029110051.86163.854210065.97168.641610080.07172.3033
10104.76181.388510115.34184.6601 10125.7 188.51910129.15189.976510142.94197.2071
10146.39197.668810153.28196.972110163.62196.694310167.07 197.64210198.04212.0999
#Mann= 3 , 0 , 0
9801.952    0.12       09801.952    0.12       010198.04    0.12       0
#XS Ineff= 2 , 0
       09932.951                       0
Bank Sta=9801.952,10198.04
Exp/Cntr=0.3,0.1

Type RM Length L Ch R = 1 ,2468.648,188.182900,188.182900,188.182900
XS GIS Cut Line= 6
1224519.89413717 636440.713892691224644.78007698636456.526617222
1224728.09613587636463.2116755251224730.09024485636463.365068468
1224801.59628788636469.7073567481224937.60109753636491.083899655
#Sta/Elev= 30
9789.533150.58839815.558149.14889832.093147.80739842.014147.47349848.628 146.449
 9868.47145.85619881.698145.07399898.234145.37679904.848144.94939924.646144.5778
9937.811145.13259954.268144.17969964.142144.540510010.23142.566810033.28142.9431
10059.63144.377810062.93144.681510076.13147.083510089.41148.902210092.74 149.736
10115.98157.128310145.87166.889110159.16170.585910169.12173.747210182.41179.0194
10195.69185.630210199.01186.501310202.33186.302310205.65185.728210210.46185.7613
#Mann= 3 , 0 , 0
9789.533    0.12       09789.533    0.12       010210.46    0.12       0
#XS Ineff= 2 , 0
       09961.822                       0
Bank Sta=9789.533,10210.46
Exp/Cntr=0.3,0.1

Type RM Length L Ch R = 1 ,2280.465,188.182800,188.182800,188.182800
XS GIS Cut Line= 6
1224450.25920904636628.630600572 1224563.3493894636646.725029424
1224692.41224265636650.6553265751224761.36963901636649.242410168
1224913.88244495 636641.21666798 1225004.3541348636638.778394967
#Sta/Elev= 30
9721.866 142.8859735.469142.70789801.921137.65749845.009136.12439871.267136.1035
9887.679 135.5419897.526134.00139943.479131.80289982.862128.545810005.83129.7753
10018.96131.002110045.23131.1727 10051.8131.800110064.94134.217510081.36136.3605
10091.22138.085610094.51139.186810107.65145.8943 10117.5149.982910120.79150.7377
10130.64151.462310183.21152.6217 10186.5153.616810209.47163.398410219.32 166.138
10229.16168.417710235.73169.351910252.14169.1551 10258.7170.794110277.72177.3951
#Mann= 3 , 0 , 0
9721.866    0.12       09721.866    0.12       010277.72    0.12       0
#XS Ineff= 2 , 0
       09946.805                       0
Bank Sta=9721.866,10277.72
Exp/Cntr=0.3,0.1

Type RM Length L Ch R = 1 ,2092.282,188.182900,188.182900,188.182900
XS GIS Cut Line= 6
1224529.42233527636812.967594609  1224702.398698 636850.41713582
1224814.41502598636819.1791522061224879.19800681 636803.80121085
 1224967.0537003636788.3916164341225041.46335053636779.811668754
#Sta/Elev= 30
9756.757126.72969770.068 125.8689813.707124.45539830.491121.99099833.848121.9049
9843.918122.92239864.059123.1485  9884.2122.49099897.628120.81689924.482120.9805
9937.967120.12529948.176120.38739968.593119.68989982.205118.44929995.816116.1668
10019.69118.854310040.14122.340710060.48123.665210107.69128.5457 10151.1134.4719
10167.76134.996210174.42135.643910187.74  137.9710201.07139.564110207.71141.1407
10220.92143.235410227.53143.901310240.74146.192610253.95147.663810280.72154.4722
#Mann= 3 , 0 , 0
9756.757    0.12       09756.757    0.12       010280.72    0.12       0
#XS Ineff= 2 , 0
       09944.538                       0
Bank Sta=9756.757,10280.72
Exp/Cntr=0.3,0.1

Type RM Length L Ch R = 1 ,  1904.1,188.182800,188.182800,188.182800
XS GIS Cut Line= 6
 1224527.1605317636988.2573741821224760.24494305637027.498662978
1224866.88663191637001.3927471191224928.93714559636989.123757556
1224999.46418673636979.2563759241225092.61771262636971.049659804
#Sta/Elev= 30
9713.604114.55969769.014112.44049782.322113.74839808.938112.91279822.247111.6621
9845.536111.8851 9852.19111.21139858.844109.29959862.171 109.2039872.152110.1566
9887.185110.45469895.441109.97549905.422110.8172 9918.73109.59289975.641109.1154
10002.65106.954610033.07108.684910053.36108.499810116.97112.787510133.59115.1995
10150.15115.450910158.07116.840610170.03117.0465 10186.6119.353110199.81123.5675
 10206.4124.757110229.46126.7406 10255.8131.906410278.86133.137310287.74134.6274
#Mann= 3 , 0 , 0
9713.604  0.0726       09713.604  0.0726       010287.74  0.0726       0
#XS Ineff= 2 , 0
       09945.418                       0
Bank Sta=9713.604,10287.74
Exp/Cntr=0.3,0.1

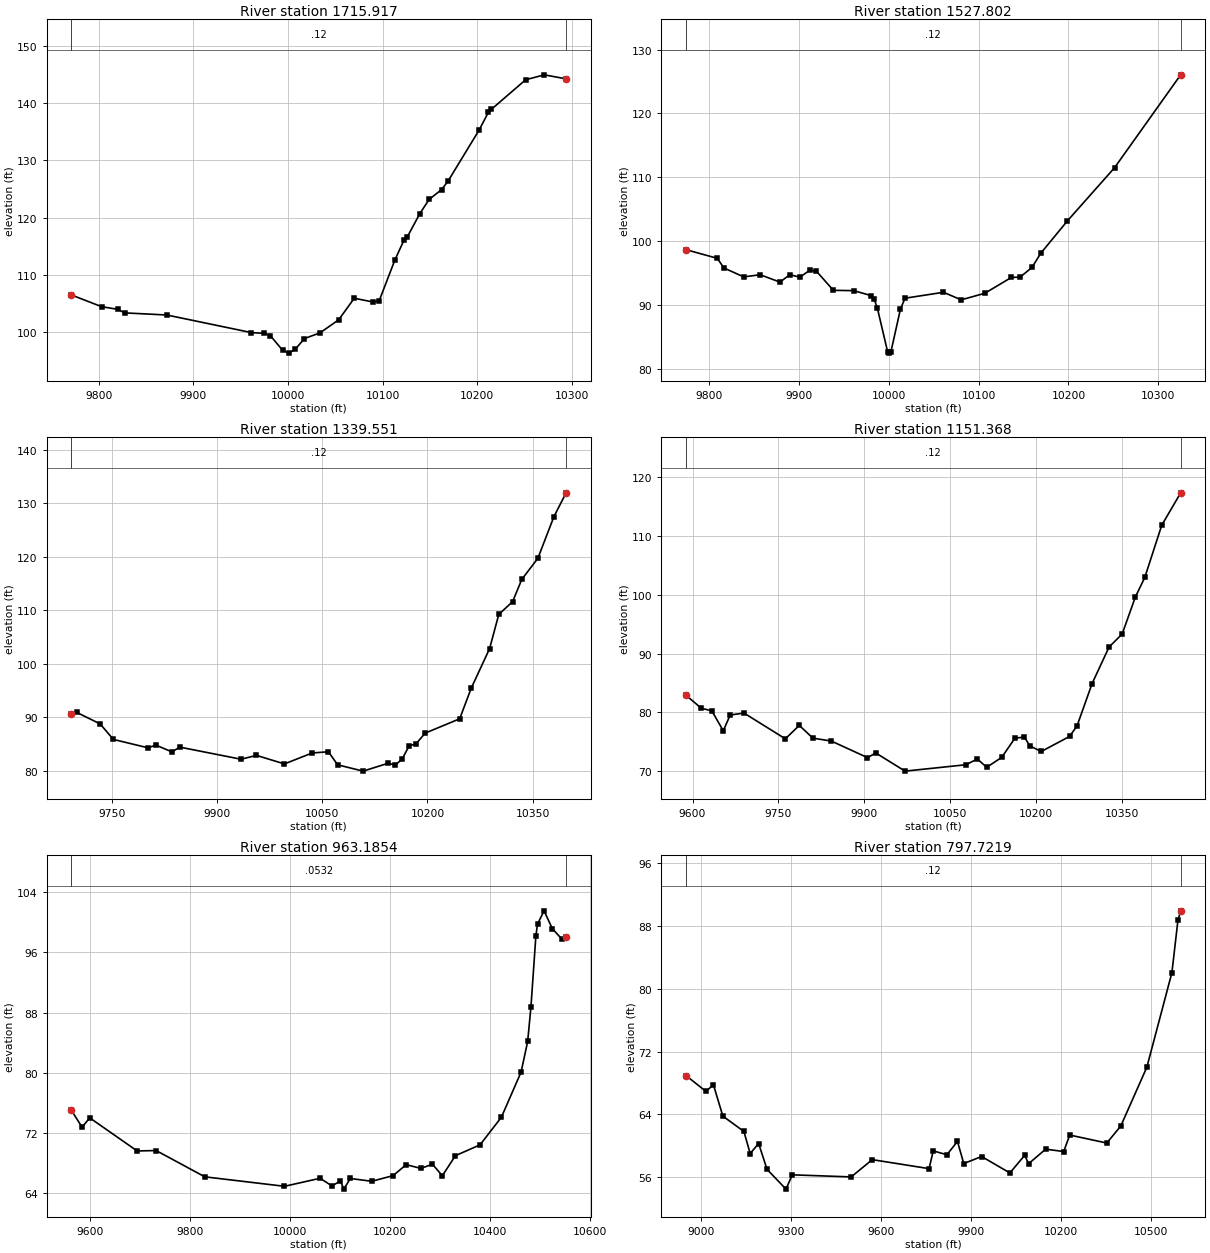
Type RM Length L Ch R = 1 ,1715.917,188.115000,188.115000,188.115000
XS GIS Cut Line= 6
 1224593.8837381 637136.40551047 1224779.4384833637194.944070593
1224814.89144164637196.5037003611224845.29848284637197.976679713
1224975.77182031637210.6673191341225106.70682415637220.866980702
#Sta/Elev= 30
9770.943106.53099802.997104.48249820.198104.02019827.078 103.4069871.801103.0373
9961.24799.965289974.57799.842319981.14699.451789994.28396.8730410000.8596.38734
10007.4297.0312510017.2798.92848 10033.799.9174210053.48102.200410069.96105.9621
10089.74105.301710096.33105.537710112.82112.6069 10122.7116.1606   10126116.6513
10139.19120.703210149.08123.193710162.26124.906310168.84126.326610201.75135.2421
10211.62138.353710214.91138.909610251.11144.061410270.86144.921810293.86144.2171
#Mann= 3 , 0 , 0
9770.943    0.12       09770.943    0.12       010293.86    0.12       0
#XS Ineff= 2 , 0
       09941.008                       0
Bank Sta=9770.943,10293.86
Exp/Cntr=0.3,0.1

Type RM Length L Ch R = 1 ,1527.802,188.250700,188.250700,188.250700
XS GIS Cut Line= 5
1224576.92021105637272.1137269291224700.18850768637334.313326135
1224777.52808169 637378.238237561224815.13080588637393.274158537
 1225098.2659426637407.821943387
#Sta/Elev= 30
9773.98898.644799808.85497.289859816.20495.780489838.25394.379299856.62794.71573
9878.676 93.56419889.70194.730299900.72594.33632 9911.7595.399249919.288  95.273
9938.153 92.27539960.79192.223679980.52391.43823 9983.4390.987739987.16689.47872
9998.52282.6854510000.4582.4365510002.2182.6061410012.8189.3042210017.9491.03861
10060.8291.9682610080.5390.7851610106.8191.8128310136.3894.2907310146.2394.34801
10159.3895.8637110169.2398.09228 10198.8103.147410251.36111.487210325.01126.0372
#Mann= 3 , 0 , 0
9773.988    0.12       09773.988    0.12       010325.01    0.12       0
#XS Ineff= 2 , 0
       09962.539        10045.84       0
Bank Sta=9773.988,10325.01
Exp/Cntr=0.3,0.1

Type RM Length L Ch R = 1 ,1339.551,188.182900,188.182900,188.182900
XS GIS Cut Line= 6
1224480.77963312 637423.35951805 1224704.7121149637553.708276078
 1224752.2994135 637561.473274411224868.62514091637575.266812891
1224996.48478028637576.3263121551225150.28742558637570.671803132
#Sta/Elev= 30
9691.67690.698839699.26990.911739732.64388.766389751.62485.856349800.97484.29226
9812.36384.78764 9835.1483.532129846.52984.417069933.84182.153429955.89282.87459
9995.78381.2755110035.4583.3249510058.5883.5473810071.7981.1070210108.1379.92885
10144.2881.4212410154.1281.0341910163.9682.2372510173.81 84.638810183.6585.03354
10196.7787.0422410245.9989.71792 10262.495.4206710288.67102.8356 10301.8109.2396
 10321.5111.620810334.63115.781510357.61119.738510380.59127.546110397.91131.9798
#Mann= 3 , 0 , 0
9691.676    0.12       09691.676    0.12       010397.91    0.12       0
#XS Ineff= 2 , 0
       09967.151        10058.78       0
Bank Sta=9691.676,10397.91
Exp/Cntr=0.3,0.1

Type RM Length L Ch R = 1 ,1151.368,188.182800,188.182800,188.182800
XS GIS Cut Line= 6
1224371.09608281637523.1739273821224621.22649756637699.461519063
1224715.21083066637744.9790897671224716.96445552637745.940754935
1224788.39884835637773.1032260061225162.72734544637793.459458485
#Sta/Elev= 30
9588.56382.921259615.56280.702939633.61180.28722 9653.6876.895779665.72179.56695
9689.80479.903319762.052  75.5349786.41477.804439810.21775.642039842.32775.15558
9905.44972.34225 9920.03 73.12759971.06570.0513410077.4271.1325610097.2372.11449
10113.6670.6990110139.9572.3965610162.9575.6489910179.3875.8227410189.23 74.3066
10208.9573.3835910258.2375.9334210271.3877.7278110297.6684.9118510327.23 91.0951
10350.2393.3291710373.2399.6015310389.66102.908610419.23111.761510452.31117.2621
#Mann= 3 , 0 , 0
9588.563    0.12       09588.563    0.12       010452.31    0.12       0
#XS Ineff= 2 , 0
       09912.854        10085.75       0
Bank Sta=9588.563,10452.31
Exp/Cntr=0.3,0.1

Type RM Length L Ch R = 1 ,963.1854,165.463500,165.463500,165.463500
XS GIS Cut Line= 6
1224284.01664388637628.3477951291224513.47243303637867.487145498
1224562.36116377637881.7520844341224616.21059442637896.062115863
1224717.49266744637922.4562782051225163.85824722637903.156933442
#Sta/Elev= 30
9562.93674.999339584.23272.777979599.73374.002569694.50769.606729732.41769.66485
9829.76166.17009 9989.1564.9100210060.37  65.97610084.1164.9622410101.06 65.6204
10107.7764.5346410120.9165.94778 10163.665.5775210206.2966.3255110232.5667.78395
10262.11 67.2896 10285.167.85245 10304.866.3085510331.0868.9823710380.3370.41976
10423.0374.0929110462.4380.0983810475.5784.1694810482.1488.7543210491.9998.18466
10495.2799.7679610508.41101.526610524.8399.1643110544.5397.7282110552.4598.11366
#Mann= 3 , 0 , 0
9562.936  0.0532       09562.936  0.0532       010552.45  0.0532       0
#XS Ineff= 2 , 0
       09922.574        10101.55       0
Bank Sta=9562.936,10552.45
Exp/Cntr=0.3,0.1

Type RM Length L Ch R = 1 ,797.7219,211.018800,211.018800,211.018800
XS GIS Cut Line= 5
1223626.88937005637689.8331501191224558.87617001638040.274754182
1224631.20349765638067.1376950141224691.14129323638069.399498612
1225197.78530136637974.403747082
#Sta/Elev= 30
8949.505 68.94949016.30566.921739040.84167.791699072.38763.786589142.489 61.8384
9163.37359.032939191.56160.304269219.60157.021689282.69354.505219303.72456.32351
 9500.0156.057489570.11258.254089759.38757.111059773.40859.364979818.97458.87742
9854.025 60.57239875.05657.756869934.64258.6531710028.7356.5642810077.9858.79619
10091.2657.7439910148.0159.5879610208.0959.2853410228.1261.3813710351.6260.36594
10398.3262.5366510485.1470.0152210568.5982.0381810588.6288.6790510597.8189.89379
#Mann= 3 , 0 , 0
8949.505    0.12       08949.505    0.12       010597.81    0.12       0
#XS Ineff= 2 , 0
       09932.673        10047.57       0
Bank Sta=8949.505,10597.81
Exp/Cntr=0.3,0.1

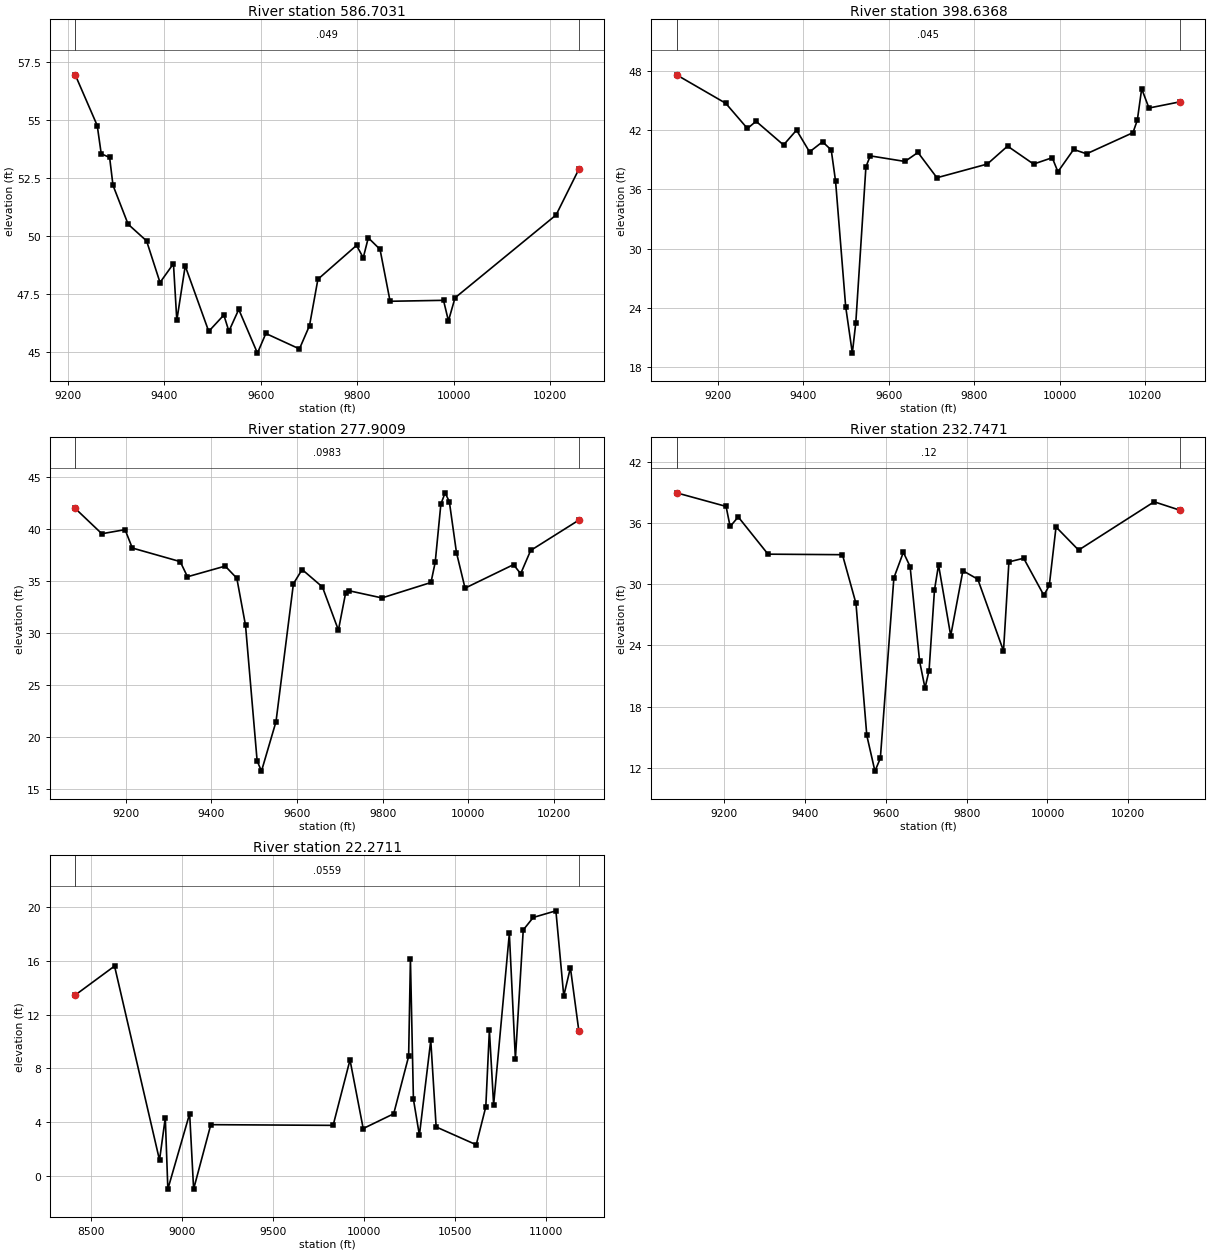
Type RM Length L Ch R = 1 ,586.7031,188.066300,188.066300,188.066300
XS GIS Cut Line= 6
1223727.21042031637946.6550386851224266.27139986638138.586880729
1224424.63011464638194.3277596091224466.68199998638205.814671144
1224564.48029119638240.1656709911224716.02113292638199.453206062
#Sta/Elev= 30
9215.30856.958329260.92354.769989269.21853.552939286.63153.391739293.59752.19254
 9324.9450.513529363.24849.792199391.10947.99716 9418.9748.810159425.93546.36312
9443.34848.712389492.10445.889429523.44746.595139533.89545.894989554.35946.83683
9593.09944.950689610.51245.797999680.16445.132329701.05946.138679718.47248.13859
9798.55749.59941 9812.4749.064789822.90449.926199847.25149.42859 9868.1247.18799
9978.88847.228969989.09246.3417510002.7847.3375710212.3150.9127710259.5652.88897
#Mann= 3 , 0 , 0
9215.308   0.049       09215.308   0.049       010259.56   0.049       0
#XS Ineff= 2 , 0
       09951.801           10096       0
Bank Sta=9215.308,10259.56
Exp/Cntr=0.3,0.1

Type RM Length L Ch R = 1 ,398.6368,120.735900,120.735900,120.735900
XS GIS Cut Line= 6
1223564.69031894638171.3741911651224403.57126379638386.377113104
1224433.66687739638390.9850787671224435.64886227638391.252914503
1224523.76782629638410.9318433551224708.10482031638358.910360381
#Sta/Elev= 30
9102.55947.591199217.76744.71174 9268.5742.160799288.89242.888629353.24240.49191
9383.724 41.99559414.20639.790689444.68840.814269465.009 39.9827 9475.1736.81822
9498.87824.115879514.44519.424379522.58622.516179546.29438.279679556.45539.38793
 9637.7438.823719668.22239.734429712.66537.175499830.79238.561829878.20840.37635
9939.17238.558779982.90839.202949996.18437.77826 10033.140.0400910063.3539.59677
10172.0441.7362110182.2743.00187 10192.546.1819110209.5444.2311410282.8344.86307
#Mann= 3 , 0 , 0
9102.559   0.045       09102.559   0.045       010282.83   0.045       0
#XS Ineff= 2 , 0
       09906.894        10094.71       0
Bank Sta=9102.559,10282.83
Exp/Cntr=0.3,0.1

Type RM Length L Ch R = 1 ,277.9009,45.153800,45.153800,45.153800
XS GIS Cut Line= 5
1223530.83604252638293.3180557791224307.76558176638492.356773257
1224383.53600258638500.2730858621224446.86650363638511.582103893
 1224676.4395698638473.131442592
#Sta/Elev= 30
9082.47841.962739144.57539.530979198.76439.923949215.69838.157539327.46136.85305
9344.39535.396289432.452 36.42089459.54635.256719479.86730.724059506.961 17.6936
9517.12116.716179550.98921.471729591.63134.724799611.951 36.09139659.366 34.4137
9696.62130.267319713.55533.852349720.32934.061819798.22533.361699912.62434.84641
 9922.5236.796469935.71542.382419945.61143.463049955.50742.606489972.11737.71732
9992.11434.3027310105.2836.5630710121.9135.68777 10145.237.9241410257.7840.84276
#Mann= 3 , 0 , 0
9082.478  0.0983       09082.478  0.0983       010257.78  0.0983       0
#XS Ineff= 2 , 0
       09943.986        10096.69       0
Bank Sta=9082.478,10257.78
Exp/Cntr=0.3,0.1

Type RM Length L Ch R = 1 ,232.7471,210.476000,210.476000,210.476000
XS GIS Cut Line= 6
1223507.08710462638362.3030657921224327.67230666638532.634588167
1224365.14390081638536.9824545981224421.89166149638548.805880174
1224587.62637821638547.177987456 1224734.8084076638554.207518801
#Sta/Elev= 30
9081.66638.941259204.216 37.61059214.26835.643089234.373 36.57969308.089  32.933
9492.38232.881249525.88928.104139552.69615.17541  9572.811.681939586.203 12.9419
9619.71130.608379643.16633.11862 9659.9231.717779683.37622.450059696.77919.82562
9706.83121.531929720.23429.421559730.28631.884649760.44324.94574  9790.631.30841
9827.45930.482359891.12323.456049904.52632.175169941.075  32.533 9991.0728.90149
10004.4929.8673210021.1835.5973210077.0633.3316510264.1538.06368 10328.737.22889
#Mann= 3 , 0 , 0
9081.666    0.12       09081.666    0.12       0 10328.7    0.12       0
#XS Ineff= 2 , 0
       09929.747                       0
Bank Sta=9081.666,10328.7
Exp/Cntr=0.3,0.1

Type RM Length L Ch R = 1 , 22.2711,0.000000,0.000000,0.000000
XS GIS Cut Line= 6
1222863.37129298638943.0014316891223314.76018187638932.584765047
1223592.53795964638824.9458761361224286.98240408638713.834765047
1225104.85963508638748.8083698751225592.41619617 638823.29617779
#Sta/Elev= 30
8414.06413.45241 8629.9315.610398876.8151.1601258908.4824.3163198922.556  -0.999
9042.1874.6221289063.959  -0.9999158.2983.8008519829.7993.7493349922.4268.623648
9994.8963.51206210162.264.611199 10244.38.88847110254.1516.1316410270.565.695718
 10303.43.01531110365.7810.0791710395.333.63162510615.332.30492310667.865.129097
10687.5910.8396310710.825.27527110797.1118.03643 10830.38.70072510873.4418.30103
10928.2719.2307411052.6619.7243911095.8113.3871711132.3215.48822 11178.910.75552
#Mann= 3 , 0 , 0
8414.064  0.0559       08414.064  0.0559       0 11178.9  0.0559       0
#XS Ineff= 2 , 0
       09924.617        10089.73       0
Bank Sta=8414.064,11178.9
Exp/Cntr=0.3,0.1